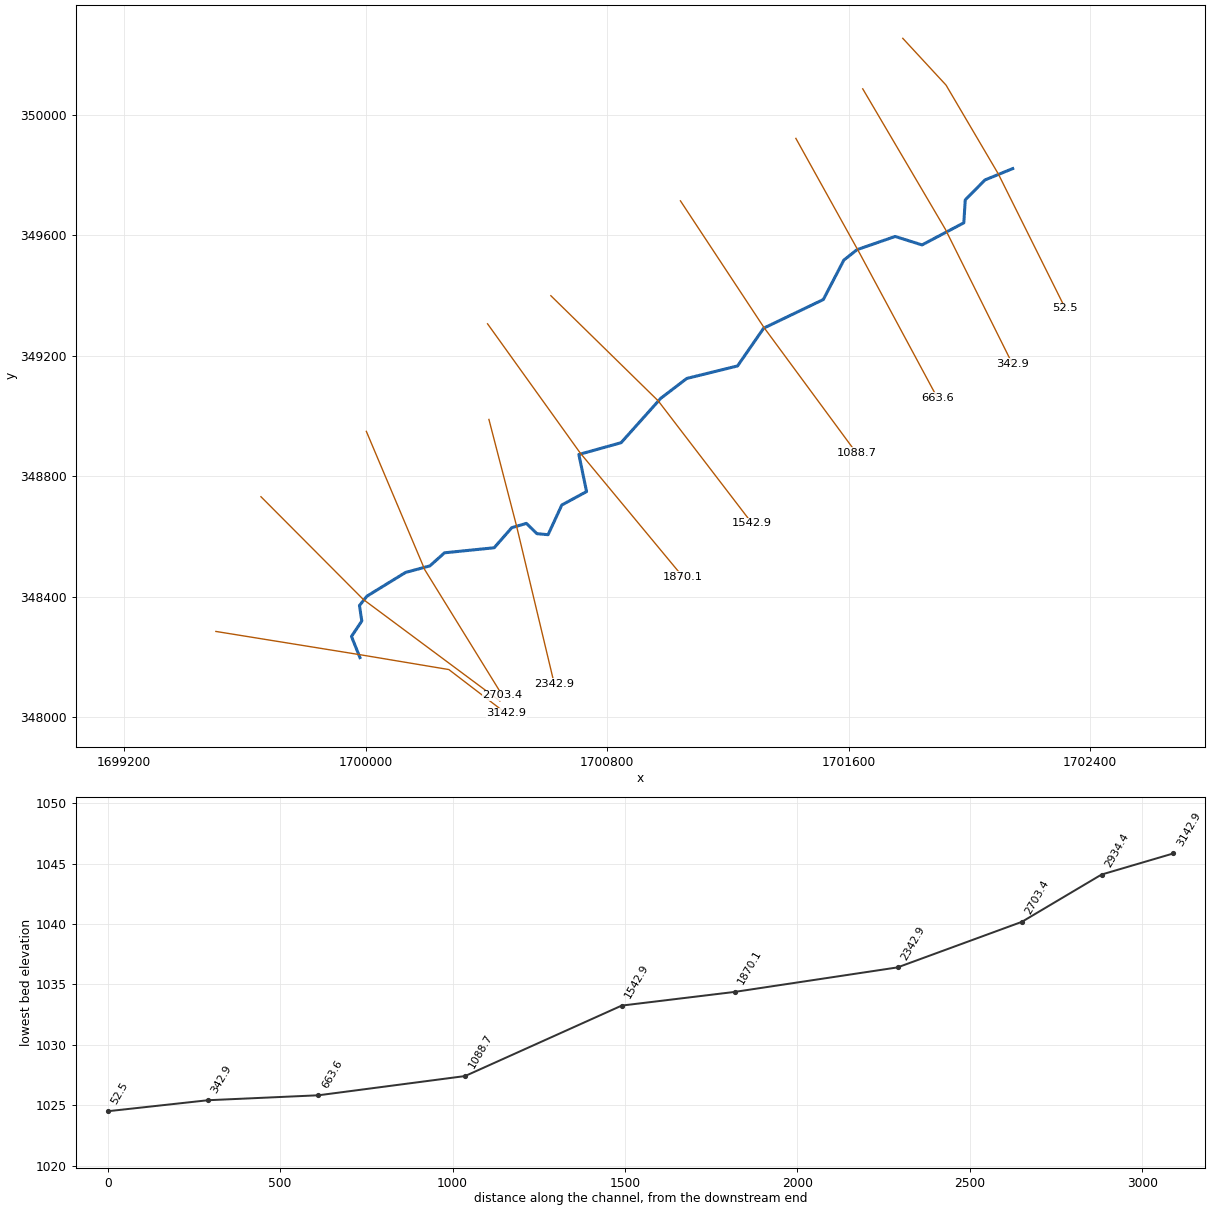
--- HarrisFk.prj (project) ---

Proj Title=HarrisFk
Current Plan=p01
Geom File=g01
Flow File=f01
Plan File=p01
DSS Export Rating Curves=0
DSS Export Rating Curve Sorted=0
DSS Export Volume Flow Curves=0
DXF OffsetX=0
DXF OffsetY=0
DXF ScaleX=0
DXF ScaleY=0

--- HarrisFk.p01 (plan) ---

Plan Title=Floodplain
Program Version=4.00
Geom File=g01
Flow File=f01
K Sum by GR=0
Std Step Tol=0.01
Critical Tol=0.01
Num of Std Step Trials=20
Max Error Tol=0.3
Flow Tol Ratio=0.001
Split Flow NTrial=30
Split Flow Tol=0.02
Split Flow Ratio=0.02
Log Output Level=0
Friction Slope Method=1
Unsteady Friction Slope Method=2
Unsteady Bridges Friction Slope Method=1
Global Log Level=0
CheckData=False
Run HTab=0
Run UNet=0
Run PostProcess=0
UNET Theta=0
UNET Theta Warmup=0
UNET ZTol=0
UNET ZSATol=0
UNET MxIter=0
UNET MaxInSteps=0
UNET DtIC=0
UNET DtMin=0
UNET MaxCRTS=0
UNET WFStab=0
UNET SFStab=0
UNET WFX=0
UNET SFX=0
UNET DSS MLevel=0
UNET DZMax Abort=0
UNET Convert EG Bridges=0
UNET Use Existing IB Tables=0
UNET Froude Limit=0
UNET Froude Power=0
Write IC File=0
Echo Input=False
Echo Output=False
Write Detailed=0

--- HarrisFk.f01 (steady flow) ---

Flow Title=NFF Regression Equation
Program Version=4.00
Number of Profiles=1
Profile Names=P100yr
River Rch & RM=HarrisFk,Main      ,3142.9
796.5905
River Rch & RM=HarrisFk,Main      ,2934.4
796.5905
River Rch & RM=HarrisFk,Main      ,2703.4
1063.697
River Rch & RM=HarrisFk,Main      ,342.9
1109.109
River Rch & RM=HarrisFk,Main      ,52.5
1112.304
Boundary for River Rch & Prof#=HarrisFk,Main      ,1
Up Type=0
Dn Type=3
Dn Slope=0.004963

--- HarrisFk.g01 (geometry) ---

Geom Title=USGS 3m DEM
Program Version=4.00

River Reach=HarrisFk     ,Main
Reach XY= 30
     1699981.045      348198.875     1699953.027      348268.921
     1699987.272      348320.288     1699979.489      348371.654
     1700004.394      348402.785     1700132.032      348481.392
     1700212.900      348503.265     1700261.306      348546.663
     1700425.719      348563.355     1700484.141      348630.122
     1700532.547      348644.310     1700567.599      348610.091
     1700604.321      348606.753     1700649.860      348705.289
     1700731.846      348749.909     1700706.311      348873.022
     1700846.221      348912.131     1700977.663      349059.435
     1701063.813      349125.425     1701232.083      349166.952
     1701318.636      349292.350     1701516.200      349387.371
     1701584.077      349518.142     1701627.891      349552.949
     1701754.226      349596.765     1701843.200      349568.674
     1701981.631      349642.058     1701986.335      349718.129
     1702051.788      349784.387     1702143.582      349822.020

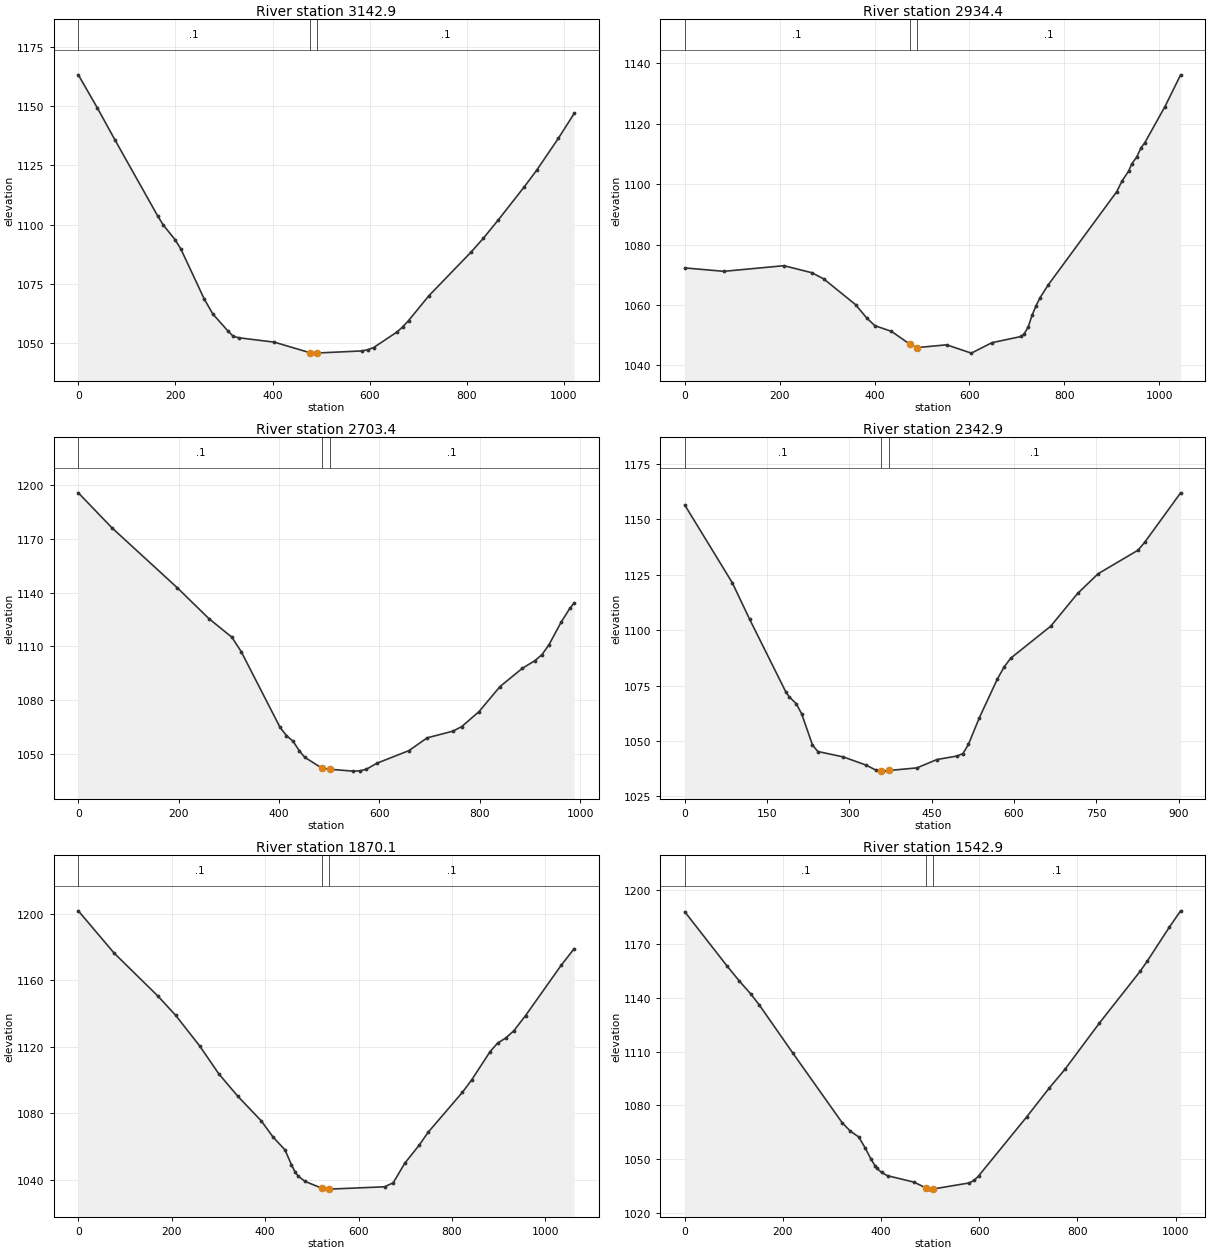
Type RM Length L Ch R = 1 ,3142.9,218.225,208.544,199.077
XS GIS Cut Line= 4
     1699503.846      348285.626     1699981.256      348208.418
     1700275.562      348159.115     1700465.328      348013.628
#Sta/Elev= 30
       0 1163.16    39.4 1149.12    76.1 1135.48   163.6 1103.61   175.0 1099.83
   199.1 1093.70   211.1 1089.75   259.2 1068.70   276.9 1062.36   307.3 1055.36
   319.3 1052.89   331.4 1052.29   403.5 1050.47   476.1 1046.06   487.7 1045.84
   491.1 1045.88   584.0 1046.77   596.1 1047.27   608.3 1048.21   656.3 1054.76
   668.3 1056.97   680.2 1059.59   721.7 1069.98   808.7 1088.42   834.1 1094.27
   865.1 1102.06   918.8 1116.06   944.2 1123.03   988.8 1136.47  1021.1 1146.86
#Mann= 3 , 0 , 0
       0     0.1       0   476.1   0.045       0   491.1     0.1       0
Bank Sta=   476.1,   491.1
Exp/Cntr=0.3,0.1

Type RM Length L Ch R = 1 ,2934.4,239.679,230.946,221.489
XS GIS Cut Line= 3
     1699653.187      348732.828     1699992.494      348391.579
     1700444.770      348054.744
#Sta/Elev= 30
       0 1072.28    82.3 1071.15   209.0 1073.01   267.7 1070.69   292.9 1068.65
   360.1 1060.11   383.7 1055.69   400.4 1053.19   435.6 1051.29   473.8 1047.12
   488.8 1045.91   552.0 1046.84   604.0 1044.09   647.3 1047.54   709.1 1049.60
   715.1 1050.41   723.9 1052.74   732.1 1056.65   740.6 1059.83   749.1 1062.48
   766.1 1066.66   910.3 1097.45   922.0 1101.13   935.7 1104.32   941.9 1106.61
   952.7 1108.99   961.8 1112.03   969.7 1113.70  1012.1 1125.63  1045.2 1136.15
#Mann= 3 , 0 , 0
       0     0.1       0   473.8   0.045       0   488.8     0.1       0
Bank Sta=   473.8,   488.8
Exp/Cntr=0.3,0.1

Type RM Length L Ch R = 1 ,2703.4,364.934,360.51,352.962
XS GIS Cut Line= 3
     1700002.286      348949.752     1700196.142      348490.020
     1700452.676      348073.721
#Sta/Elev= 30
       0 1195.79    66.9 1176.25   197.2 1142.70   260.1 1125.48   306.0 1115.04
   324.6 1106.96   401.9 1064.66   414.7 1060.07   427.6 1056.94   440.5 1051.52
   451.0 1047.94     486 1041.73     501 1041.23   547.3 1040.18   561.2 1040.33
   574.1 1041.27   594.9 1044.60   658.8 1051.66   694.9 1058.78   746.7 1062.57
   763.9 1065.09   798.3 1073.45   840.1 1087.46   884.7 1097.67   909.9 1102.00
   923.8 1105.33   937.8 1110.90   962.4 1123.69   979.5 1131.29   987.9 1134.19
#Mann= 3 , 0 , 0
       0     0.1       0     486   0.045       0     501     0.1       0
Bank Sta=     486,     501
Exp/Cntr=0.3,0.1

Type RM Length L Ch R = 1 ,2342.9,464.269,472.823,480.285
XS GIS Cut Line= 3
     1700408.398      348989.342     1700499.982      348635.402
     1700624.836      348111.851
#Sta/Elev= 30
       0 1156.48    86.6 1121.41   118.4 1104.84   184.0 1072.23   190.4 1069.95
   203.5 1066.74   213.2 1062.15   232.7 1048.25   242.5 1045.26   288.5 1042.85
   330.2 1039.16   349.0 1036.80   358.1 1036.48   362.1 1036.41   373.1 1036.72
   423.1 1037.87   459.7 1041.65   496.3 1043.23   507.1 1044.34   517.0 1048.48
   536.7 1060.40   569.6 1077.90   581.8 1083.29   594.0 1087.36   667.2 1101.86
   716.0 1116.60   753.5 1125.50   825.9 1136.08   838.1 1139.60   903.8 1162.00
#Mann= 3 , 0 , 0
       0     0.1       0   358.1   0.045       0   373.1     0.1       0
Bank Sta=   358.1,   373.1
Exp/Cntr=0.3,0.1

Type RM Length L Ch R = 1 ,1870.1,323.13,327.177,326.458
XS GIS Cut Line= 3
     1700403.858      349306.786     1700710.555      348878.339
     1701051.473      348466.281
#Sta/Elev= 30
       0 1201.73    76.4 1176.39   170.3 1150.51   208.2 1138.96   260.0 1120.43
   300.8 1103.70   341.6 1090.20   391.5 1075.51   417.0 1065.69   442.6 1057.95
   456.4 1048.99   464.0 1044.83   471.0 1042.09   485.6 1039.02     521 1034.96
     536 1034.38   655.7 1035.78   674.3 1038.21   699.1 1050.00   729.9 1060.84
   748.8 1068.50   822.4 1092.60   841.9 1099.90   881.8 1117.13   897.8 1122.19
   915.6 1125.34   932.4 1129.57   957.7 1138.77  1033.6 1168.86  1061.7 1178.99
#Mann= 3 , 0 , 0
       0     0.1       0     521   0.045       0     536     0.1       0
Bank Sta=     521,     536
Exp/Cntr=0.3,0.1

Type RM Length L Ch R = 1 ,1542.9,458.818,454.224,453.864
XS GIS Cut Line= 3
     1700613.524      349400.120     1700969.518      349050.645
     1701280.122      348644.322
#Sta/Elev= 30
       0 1188.04    85.7 1157.94   110.9 1149.48   134.6 1142.14   151.2 1136.28
   220.0 1109.25   320.8 1070.28   337.6 1065.55   354.4 1062.40   367.5 1056.26
   379.6 1049.93   388.0 1046.15   391.9 1044.81   400.8 1042.56   413.1 1040.73
   467.3 1037.14   491.4 1033.90   497.1 1033.25   506.4 1033.35   579.1 1036.68
   590.2 1038.27   598.6 1040.61   696.4 1073.49   742.7 1089.71   774.6 1100.12
   844.3 1125.76   927.6 1154.76   942.5 1160.59   987.3 1179.47  1010.3 1188.58
#Mann= 3 , 0 , 0
       0     0.1       0   491.4   0.045       0   506.4     0.1       0
Bank Sta=   491.4,   506.4
Exp/Cntr=0.3,0.1

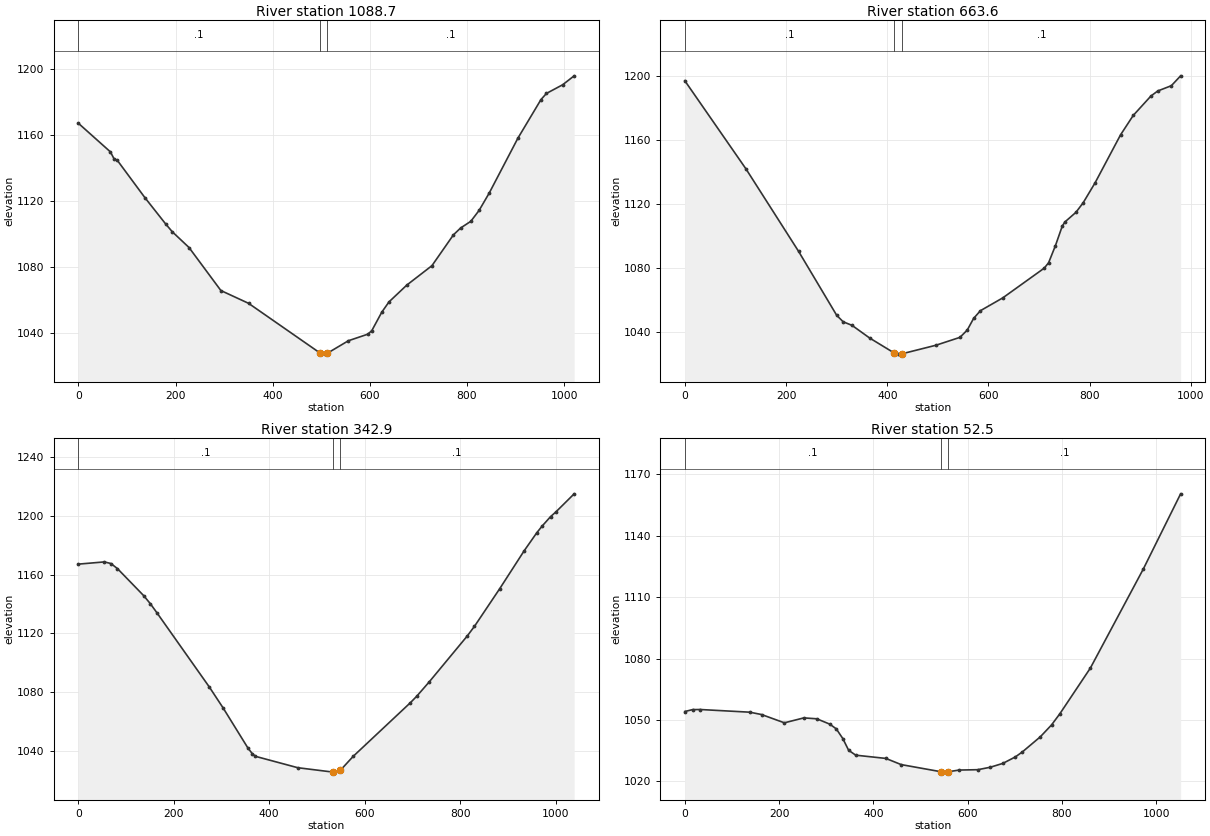
Type RM Length L Ch R = 1 ,1088.7,426.92,425.095,422.099
XS GIS Cut Line= 3
     1701042.803      349714.985     1701319.119      349295.194
     1701625.874      348877.877
#Sta/Elev= 30
       0 1167.38    66.0 1150.02    73.5 1145.82    80.2 1144.90   137.0 1122.27
   179.7 1106.34   193.5 1101.55   227.8 1092.05   293.4 1065.96   350.3 1058.23
   497.4 1028.11   506.8 1027.42   512.4 1027.94   555.8 1035.53   595.9 1039.52
   604.0 1041.65   624.6 1052.87   639.4 1059.08   676.1 1069.28   727.8 1081.04
   772.0 1099.71   786.7 1103.85   807.8 1107.93   824.8 1114.51   845.7 1125.06
   904.6 1158.26   952.2 1181.72   963.5 1185.45   996.8 1190.69  1020.5 1196.11
#Mann= 3 , 0 , 0
       0     0.1       0   497.4   0.045       0   512.4     0.1       0
Bank Sta=   497.4,   512.4
Exp/Cntr=0.3,0.1

Type RM Length L Ch R = 1 ,663.6,319.365,320.681,320.111
XS GIS Cut Line= 3
     1701425.227      349922.358     1701636.791      349540.529
     1701893.595      349061.989
#Sta/Elev= 30
       0 1197.26   120.8 1141.99   224.9 1090.22   300.1 1050.17   312.9 1046.11
   330.4 1043.87   365.3 1035.91   414.1 1026.48   422.2 1025.83   429.1 1026.04
   496.1 1031.40   543.6 1036.34   558.0 1040.90   570.6 1048.21   584.0 1053.05
   628.1 1061.07   710.2 1079.75   718.8 1083.15   732.3 1093.88   745.7 1106.06
   750.9 1108.68   772.7 1114.72   786.9 1120.65   810.7 1133.30   860.9 1163.31
   886.0 1175.50   920.9 1187.65   934.4 1190.82   961.3 1194.14   979.6 1200.32
#Mann= 3 , 0 , 0
       0     0.1       0   414.1   0.045       0   429.1     0.1       0
Bank Sta=   414.1,   429.1
Exp/Cntr=0.3,0.1

Type RM Length L Ch R = 1 ,342.9,290.568,290.372,290.214
XS GIS Cut Line= 3
     1701646.771      350086.779     1701920.476      349620.655
     1702142.367      349174.251
#Sta/Elev= 30
       0 1167.20    54.5 1168.71    68.3 1167.61    82.0 1164.14   137.1 1145.67
   150.9 1140.22   164.6 1134.09   274.8 1083.31   303.8 1068.98   355.8 1041.65
   364.5 1038.05   371.1 1036.19   459.9 1028.43     533 1025.47   536.4 1025.42
     548 1026.69   549.8 1026.91   576.3 1036.26   695.6 1072.65   708.9 1077.05
   735.4 1086.94   815.0 1118.20   830.2 1124.81   883.3 1150.56   934.3 1176.28
   960.8 1188.59   971.9 1193.11   989.6 1199.56  1000.6 1202.72  1039.1 1215.12
#Mann= 3 , 0 , 0
       0     0.1       0     533   0.045       0     548     0.1       0
Bank Sta=     533,     548
Exp/Cntr=0.3,0.1

Type RM Length L Ch R = 1 ,52.5,59.674,52.526,46.728
XS GIS Cut Line= 4
     1701779.457      350254.448     1701922.770      350099.125
     1702096.010      349804.095     1702317.900      349357.691
#Sta/Elev= 30
       0 1054.13    16.5 1055.06    33.0 1055.11   138.0 1053.80   162.8 1052.66
   211.3 1048.61   252.6 1051.02   280.1 1050.57   307.7 1047.95   321.4 1045.65
   335.2 1040.94   347.6 1035.19   362.7 1032.79   426.6 1031.21   459.1 1028.19
   543.6 1024.70   548.0 1024.51   558.6 1024.68   581.9 1025.52   621.7 1025.70
   648.2 1026.90   674.8 1028.78   701.3 1031.94   716.2 1034.38   754.3 1041.77
   778.1 1047.57   795.9 1053.08   860.4 1075.33   973.0 1123.85  1052.0 1160.52
#Mann= 3 , 0 , 0
       0     0.1       0   543.6   0.045       0   558.6     0.1       0
Bank Sta=   543.6,   558.6
Exp/Cntr=0.3,0.1